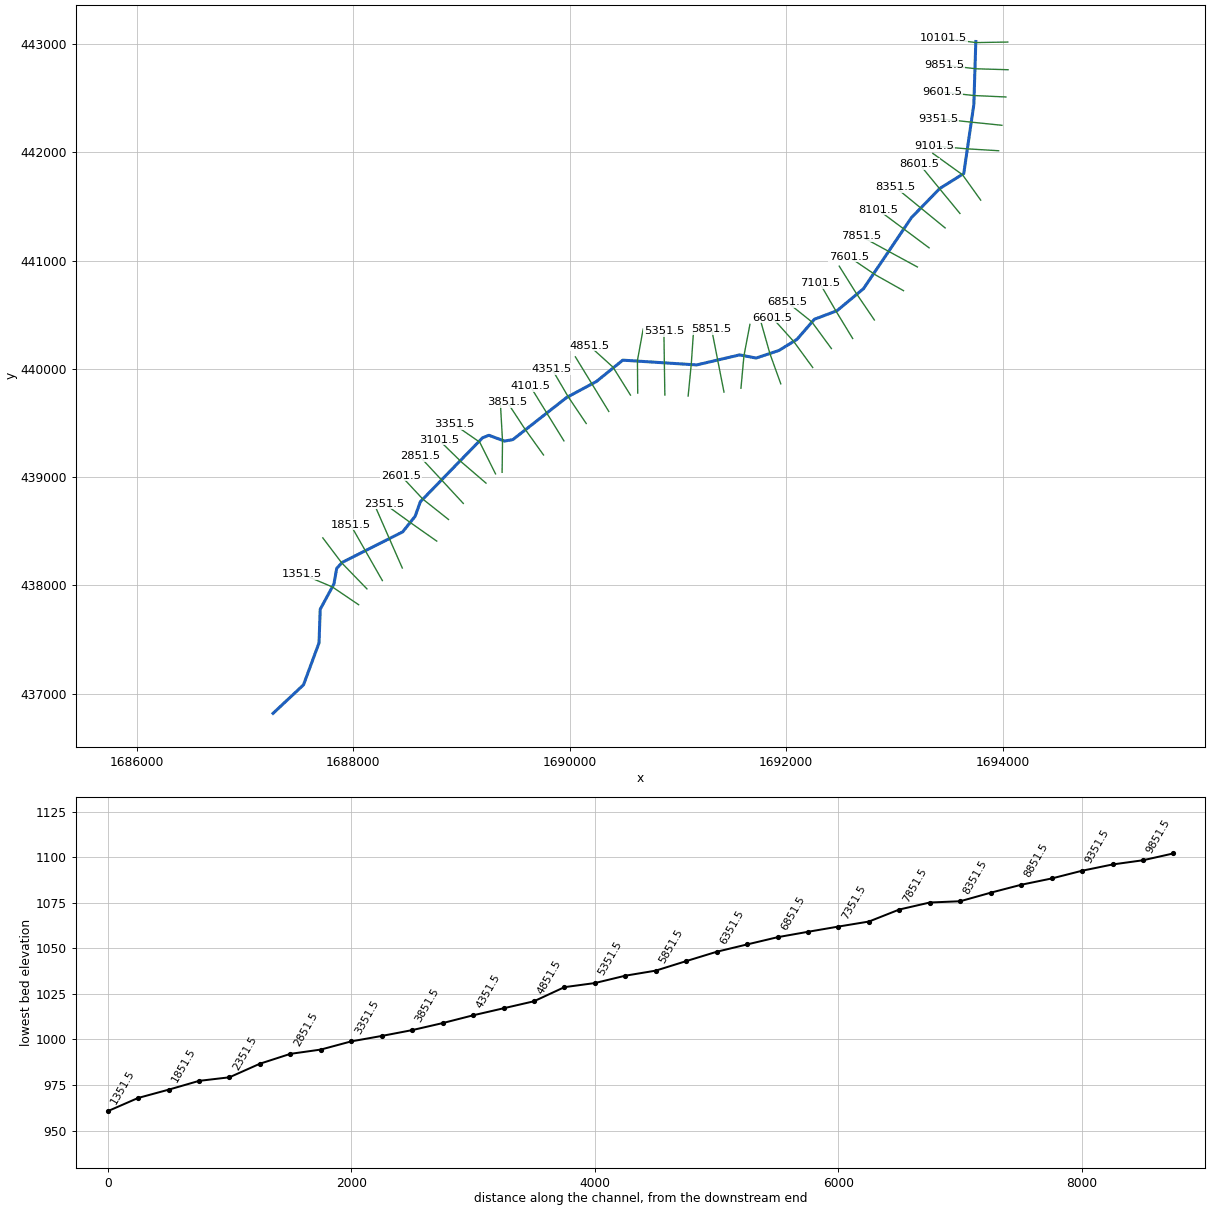
--- BROWNSRN.prj (project) ---

Proj Title=BROWNSRN
Current Plan=p01
Geom File=g01
Flow File=f01
Plan File=p01
DSS Export Rating Curves=0
DSS Export Rating Curve Sorted=0
DSS Export Volume Flow Curves=0
DXF OffsetX=0
DXF OffsetY=0
DXF ScaleX=0
DXF ScaleY=0

--- BROWNSRN.p01 (plan) ---

Plan Title=Floodplain
Program Version=4.00
Geom File=g01
Flow File=f01
K Sum by GR=0
Std Step Tol=0.01
Critical Tol=0.01
Num of Std Step Trials=20
Max Error Tol=0.3
Flow Tol Ratio=0.001
Split Flow NTrial=30
Split Flow Tol=0.02
Split Flow Ratio=0.02
Log Output Level=0
Friction Slope Method=1
Unsteady Friction Slope Method=2
Unsteady Bridges Friction Slope Method=1
Global Log Level=0
CheckData=False
Run HTab=0
Run UNet=0
Run PostProcess=0
UNET Theta=0
UNET Theta Warmup=0
UNET ZTol=0
UNET ZSATol=0
UNET MxIter=0
UNET MaxInSteps=0
UNET DtIC=0
UNET DtMin=0
UNET MaxCRTS=0
UNET WFStab=0
UNET SFStab=0
UNET WFX=0
UNET SFX=0
UNET DSS MLevel=0
UNET DZMax Abort=0
UNET Convert EG Bridges=0
UNET Use Existing IB Tables=0
UNET Froude Limit=0
UNET Froude Power=0
Write IC File=0
Echo Input=False
Echo Output=False
Write Detailed=0

--- BROWNSRN.f01 (steady flow) ---

Flow Title=Flow
Program Version=4.00
Number of Profiles=1
Profile Names=F01pct
River Rch & RM=BROWNSRN,Main      ,10101.5
544.5339
River Rch & RM=BROWNSRN,Main      ,9851.5
575.7786
River Rch & RM=BROWNSRN,Main      ,9351.5
580.0884
River Rch & RM=BROWNSRN,Main      ,9101.5
583.9444
River Rch & RM=BROWNSRN,Main      ,8851.5
618.2300
River Rch & RM=BROWNSRN,Main      ,8601.5
620.2680
River Rch & RM=BROWNSRN,Main      ,8351.5
628.5023
River Rch & RM=BROWNSRN,Main      ,7851.5
649.3705
River Rch & RM=BROWNSRN,Main      ,7601.5
652.7084
River Rch & RM=BROWNSRN,Main      ,7351.5
657.1238
River Rch & RM=BROWNSRN,Main      ,7101.5
667.4340
River Rch & RM=BROWNSRN,Main      ,6851.5
685.7463
River Rch & RM=BROWNSRN,Main      ,6351.5
689.6099
River Rch & RM=BROWNSRN,Main      ,6101.5
698.0559
River Rch & RM=BROWNSRN,Main      ,5851.5
708.2558
River Rch & RM=BROWNSRN,Main      ,5601.5
714.9519
River Rch & RM=BROWNSRN,Main      ,5351.5
802.5175
River Rch & RM=BROWNSRN,Main      ,4851.5
806.6464
River Rch & RM=BROWNSRN,Main      ,4351.5
818.6605
River Rch & RM=BROWNSRN,Main      ,4101.5
823.1814
River Rch & RM=BROWNSRN,Main      ,3851.5
838.1654
River Rch & RM=BROWNSRN,Main      ,3351.5
841.6927
River Rch & RM=BROWNSRN,Main      ,3101.5
843.0718
River Rch & RM=BROWNSRN,Main      ,2851.5
930.7042
River Rch & RM=BROWNSRN,Main      ,2601.5
935.5295
River Rch & RM=BROWNSRN,Main      ,2351.5
940.8602
River Rch & RM=BROWNSRN,Main      ,1851.5
945.1724
River Rch & RM=BROWNSRN,Main      ,1601.5
970.1730
River Rch & RM=BROWNSRN,Main      ,1351.5
972.8123
River Rch & RM=BROWNSRN,Main      ,1101.5
983.7032
River Rch & RM=BROWNSRN,Main      ,851.5
987.2991
River Rch & RM=BROWNSRN,Main      ,351.5
991.1914
Boundary for River Rch & Prof#=BROWNSRN,Main      ,1
Up Type=0
Dn Type=3
Dn Slope=0.014857

--- BROWNSRN.g01 (geometry) ---

Geom Title=Geometry
Program Version=4.00

River Reach=BROWNSRN     ,Main
Reach XY= 30
     1693752.062      443024.723     1693733.716      442441.912
     1693640.705      441805.341     1693418.844      441666.678
     1693157.731      441398.312     1692714.249      440741.289
     1692469.588      440537.961     1692260.260      440458.630
     1692100.931      440273.968     1691933.602      440170.637
     1691722.274      440100.639     1691570.945      440129.971
     1691173.622      440037.307     1690490.973      440081.306
     1690248.312      439884.644     1689973.653      439737.315
     1689475.666      439347.325     1689397.668      439333.992
     1689254.338      439387.324     1689195.006      439363.324
     1688620.828      438773.219     1688573.043      438639.147
     1688458.085      438495.244     1687900.497      438213.720
     1687848.889      438158.835     1687822.948      438013.840
     1687696.248      437780.101     1687685.326      437469.633
     1687541.970      437082.161     1687260.477      436818.658

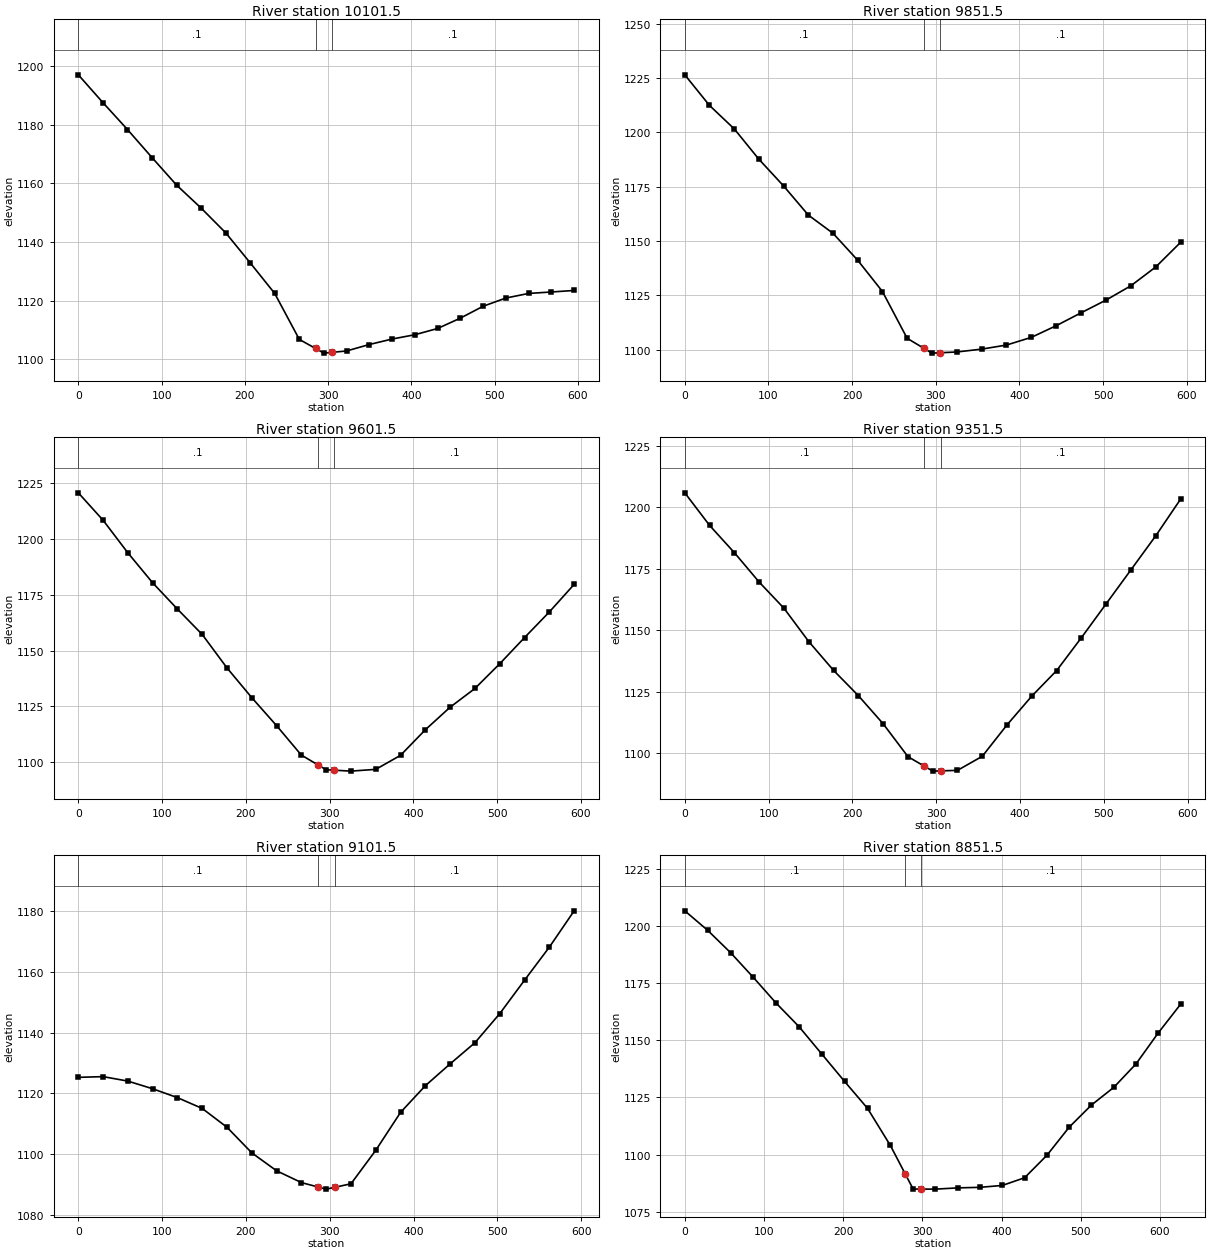
Type RM Length L Ch R = 1 ,10101.5,249.2,250,250.6
XS GIS Cut Line= 3
     1694047.230      443019.639     1693752.395      443014.729
     1693454.319      443053.966
#Sta/Elev= 24
       0 1196.99    29.5 1187.53    59.0 1178.35    88.5 1168.79   118.0 1159.40
   147.4 1151.59   176.9 1143.17   206.4 1132.91   235.9 1122.46   265.4 1106.81
   284.9 1103.72   294.9 1102.13   304.9 1102.40   322.2 1102.87   349.5 1105.07
   376.9 1106.94   404.2 1108.40   431.5 1110.53   458.9 1114.07   486.2 1118.11
   513.5 1120.91   540.9 1122.48   568.2 1122.97   595.5 1123.49
#Mann= 3 , 0 , 0
       0     0.1       0   284.9   0.045       0   304.9     0.1       0
Bank Sta=284.9,304.9
Exp/Cntr=0.3,0.1

Type RM Length L Ch R = 1 ,9851.5,250.3,250,249.9
XS GIS Cut Line= 3
     1694049.803      442764.055     1693754.539      442772.738
     1693459.122      442806.837
#Sta/Elev= 23
       0 1226.45    29.5 1212.37    59.1 1201.58    88.6 1187.60   118.2 1175.27
   147.7 1161.90   177.2 1153.52   206.8 1141.08   236.3 1126.72   265.8 1105.21
   285.4 1100.68   295.4 1098.37   305.4 1098.55   325.1 1098.89   354.9 1100.21
   384.6 1102.09   414.3 1105.62   444.1 1111.00   473.8 1116.92   503.6 1122.78
   533.3 1129.36   563.0 1138.00   592.8 1149.36
#Mann= 3 , 0 , 0
       0     0.1       0   285.4   0.045       0   305.4     0.1       0
Bank Sta=285.4,305.4
Exp/Cntr=0.3,0.1

Type RM Length L Ch R = 1 ,9601.5,251,250,249.9
XS GIS Cut Line= 3
     1694029.696      442512.276     1693734.180      442525.758
     1693439.744      442557.872
#Sta/Elev= 23
       0 1220.54    29.6 1208.26    59.2 1193.67    88.8 1180.26   118.3 1168.55
   147.9 1157.19   177.5 1142.22   207.1 1128.92   236.7 1116.40   266.2 1103.26
   285.8 1098.91   295.8 1096.69   305.8 1096.48   325.4 1096.06   355.1 1096.85
   384.7 1103.12   414.3 1114.56   443.9 1124.65   473.5 1133.02   503.2 1144.11
   532.8 1155.81   562.4 1167.27   592.0 1179.60
#Mann= 3 , 0 , 0
       0     0.1       0   285.8   0.045       0   305.8     0.1       0
Bank Sta=285.8,305.8
Exp/Cntr=0.3,0.1

Type RM Length L Ch R = 1 ,9351.5,248.9,250,250.4
XS GIS Cut Line= 3
     1693993.052      442250.772     1693698.861      442281.100
     1693404.671      442311.428
#Sta/Elev= 23
       0 1205.80    29.6 1192.54    59.2 1181.44    88.7 1169.51   118.3 1158.86
   147.9 1145.30   177.4 1133.62   207.0 1123.33   236.6 1111.89   266.2 1098.51
   285.8 1094.61   295.8 1092.62   305.8 1092.73   325.3 1092.93   354.9 1098.66
   384.5 1111.47   414.0 1123.15   443.6 1133.52   473.2 1146.92   502.8 1160.74
   532.4 1174.56   561.9 1188.36   591.5 1203.25
#Mann= 3 , 0 , 0
       0     0.1       0   285.8   0.045       0   305.8     0.1       0
Bank Sta=285.8,305.8
Exp/Cntr=0.3,0.1

Type RM Length L Ch R = 1 ,9101.5,272.3,250,236.3
XS GIS Cut Line= 3
     1693962.686      442015.708     1693667.506      442033.599
     1693372.658      442058.630
#Sta/Elev= 23
       0 1125.23    29.6 1125.46    59.1 1123.99    88.7 1121.46   118.3 1118.53
   147.9 1114.96   177.4 1108.76   207.0 1100.32   236.6 1094.41   266.2 1090.52
   285.7 1089.10   295.7 1088.37   305.7 1088.96   325.3 1090.13   354.9 1101.18
   384.5 1113.69   414.1 1122.48   443.7 1129.69   473.3 1136.67   502.9 1146.26
   532.4 1157.26   562.0 1168.16   591.6 1180.13
#Mann= 3 , 0 , 0
       0     0.1       0   285.7   0.045       0   305.7     0.1       0
Bank Sta=285.7,305.7
Exp/Cntr=0.3,0.1

Type RM Length L Ch R = 1 ,8851.5,247.8,250,241.9
XS GIS Cut Line= 3
     1693797.217      441559.400     1693629.269      441793.771
     1693355.210      441991.000
#Sta/Elev= 25
       0 1206.53    28.8 1198.04    57.7 1188.28    86.5 1177.45   115.3 1166.20
   144.2 1155.92   173.0 1143.93   201.8 1131.96   230.7 1120.22   259.5 1104.02
   278.3 1091.57   288.3 1084.95   298.3 1084.94   316.5 1084.92   344.6 1085.46
   372.8 1085.71   400.9 1086.53   429.0 1089.89   457.2 1099.71   485.3 1111.99
   513.4 1121.67   541.6 1129.38   569.7 1139.65   597.8 1153.21   626.0 1165.72
#Mann= 3 , 0 , 0
       0     0.1       0   278.3   0.045       0   298.3     0.1       0
Bank Sta=278.3,298.3
Exp/Cntr=0.3,0.1

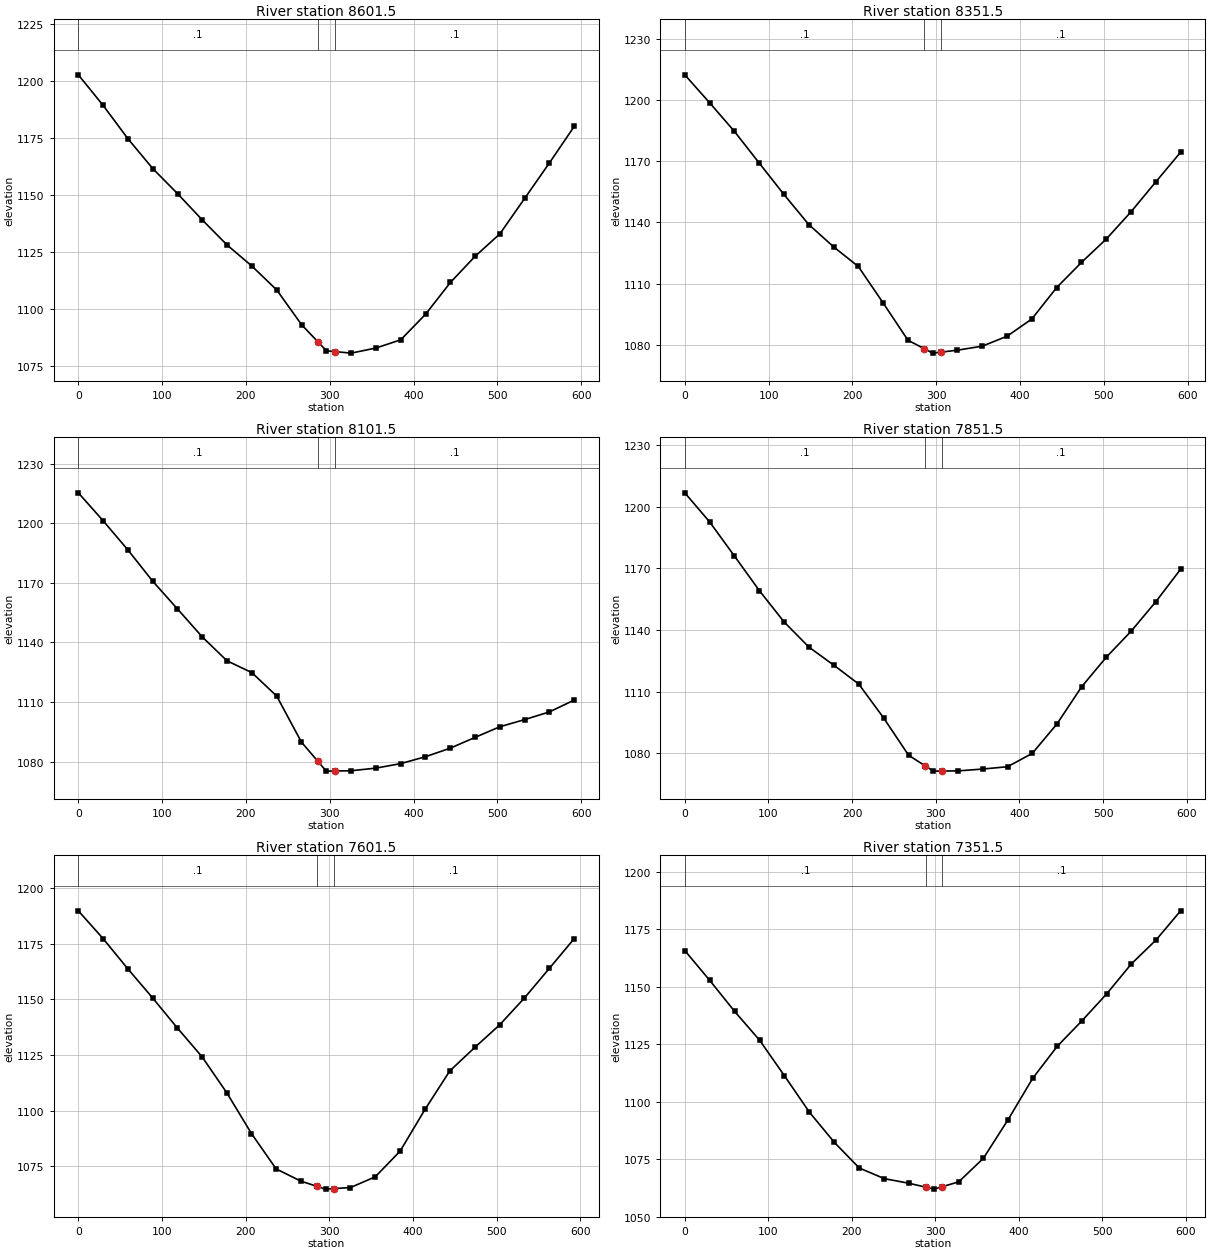
Type RM Length L Ch R = 1 ,8601.5,245,250,254.9
XS GIS Cut Line= 3
     1693605.350      441436.612     1693417.117      441665.134
     1693229.597      441893.628
#Sta/Elev= 23
       0 1202.79    29.6 1189.36    59.2 1174.71    88.8 1161.63   118.4 1150.60
   148.0 1139.02   177.6 1128.02   207.2 1118.77   236.8 1108.28   266.5 1092.99
   286.1 1085.44   296.1 1081.59   306.1 1081.24   325.6 1080.57   355.2 1082.82
   384.7 1086.43   414.3 1097.64   443.9 1111.59   473.4 1123.08   503.0 1132.96
   532.5 1148.50   562.1 1164.11   591.6 1180.10
#Mann= 3 , 0 , 0
       0     0.1       0   286.1   0.045       0   306.1     0.1       0
Bank Sta=286.1,306.1
Exp/Cntr=0.3,0.1

Type RM Length L Ch R = 1 ,8351.5,248.7,250,251
XS GIS Cut Line= 3
     1693468.529      441302.979     1693239.631      441490.258
     1693010.732      441677.537
#Sta/Elev= 23
       0 1212.44    29.6 1198.74    59.2 1184.68    88.7 1169.19   118.3 1153.72
   147.9 1138.98   177.4 1128.07   207.0 1118.39   236.6 1100.51   266.2 1082.22
   285.8 1078.02   295.8 1075.88   305.8 1076.37   325.3 1077.33   354.9 1079.30
   384.5 1084.19   414.0 1092.64   443.6 1108.04   473.2 1120.39   502.8 1131.86
   532.4 1145.26   561.9 1159.90   591.5 1174.48
#Mann= 3 , 0 , 0
       0     0.1       0   285.8   0.045       0   305.8     0.1       0
Bank Sta=285.8,305.8
Exp/Cntr=0.3,0.1

Type RM Length L Ch R = 1 ,8101.5,246.3,250,253.4
XS GIS Cut Line= 3
     1693320.606      441118.738     1693083.525      441295.544
     1692846.444      441472.351
#Sta/Elev= 23
       0 1215.34    29.6 1201.27    59.2 1186.55    88.7 1170.83   118.3 1156.85
   147.9 1142.75   177.4 1130.73   207.0 1124.79   236.6 1113.00   266.2 1089.77
   285.8 1080.11   295.8 1075.18   305.8 1075.24   325.3 1075.36   354.9 1076.69
   384.5 1078.96   414.0 1082.42   443.6 1086.72   473.2 1092.16   502.8 1097.52
   532.4 1101.13   561.9 1104.99   591.5 1110.96
#Mann= 3 , 0 , 0
       0     0.1       0   285.8   0.045       0   305.8     0.1       0
Bank Sta=285.8,305.8
Exp/Cntr=0.3,0.1

Type RM Length L Ch R = 1 ,7851.5,250.3,250,247.5
XS GIS Cut Line= 3
     1693212.287      440942.122     1692951.198      441083.809
     1692691.763      441225.320
#Sta/Elev= 23
       0 1206.74    29.7 1192.58    59.4 1175.95    89.1 1159.17   118.8 1143.86
   148.5 1131.63   178.2 1122.86   207.9 1113.70   237.6 1097.25   267.4 1079.10
   287.1 1073.95   297.1 1071.34   307.1 1071.38   326.6 1071.45   356.2 1072.36
   385.7 1073.48   415.3 1079.98   444.8 1094.30   474.4 1112.44   503.9 1126.83
   533.5 1139.44   563.0 1153.78   592.6 1169.58
#Mann= 3 , 0 , 0
       0     0.1       0   287.1   0.045       0   307.1     0.1       0
Bank Sta=287.1,307.1
Exp/Cntr=0.3,0.1

Type RM Length L Ch R = 1 ,7601.5,261.3,250,239.3
XS GIS Cut Line= 3
     1693083.942      440723.293     1692826.373      440868.178
     1692580.788      441035.277
#Sta/Elev= 23
       0 1189.83    29.6 1177.34    59.1 1163.78    88.7 1150.72   118.2 1137.23
   147.8 1124.25   177.3 1108.12   206.9 1089.73   236.4 1073.82   266.0 1068.32
   285.5 1065.95   295.5 1064.73   305.5 1064.97   325.2 1065.43   354.9 1070.27
   384.6 1081.82   414.3 1100.53   444.0 1117.89   473.8 1128.41   503.4 1138.51
   533.2 1150.66   562.9 1163.94   592.6 1177.30
#Mann= 3 , 0 , 0
       0     0.1       0   285.5   0.045       0   305.5     0.1       0
Bank Sta=285.5,305.5
Exp/Cntr=0.3,0.1

Type RM Length L Ch R = 1 ,7351.5,251,250,249
XS GIS Cut Line= 3
     1692814.927      440452.393     1692647.153      440699.385
     1692490.447      440949.619
#Sta/Elev= 23
       0 1165.67    29.9 1152.69    59.7 1139.22    89.6 1126.70   119.4 1111.22
   149.3 1095.38   179.2 1082.26   209.0 1071.15   238.9 1066.54   268.7 1064.51
   288.6 1062.83   298.6 1061.98   308.6 1063.06   328.1 1065.16   357.6 1075.39
   387.2 1092.19   416.7 1110.18   446.2 1124.13   475.7 1135.17   505.3 1146.88
   534.8 1159.88   564.3 1170.24   593.8 1182.94
#Mann= 3 , 0 , 0
       0     0.1       0   288.6   0.045       0   308.6     0.1       0
Bank Sta=288.6,308.6
Exp/Cntr=0.3,0.1

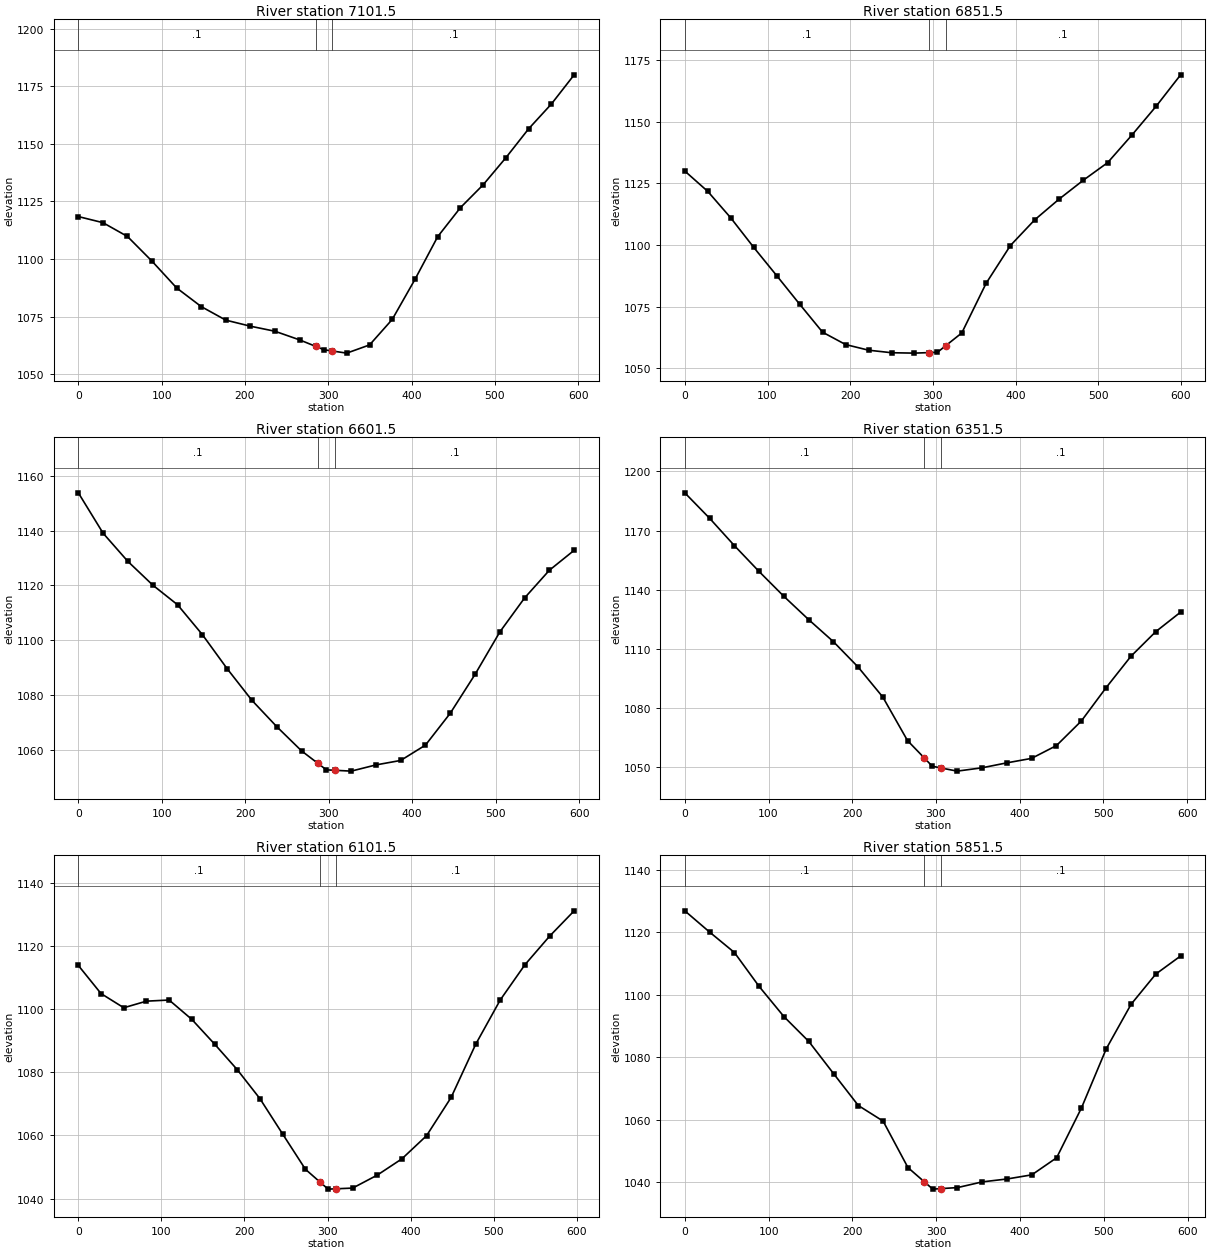
Type RM Length L Ch R = 1 ,7101.5,247.5,250,259
XS GIS Cut Line= 3
     1692614.789      440281.037     1692461.426      440532.993
     1692310.543      440792.549
#Sta/Elev= 24
       0 1118.41    29.5 1115.77    59.0 1109.76    88.5 1099.02   118.0 1087.42
   147.5 1079.33   177.0 1073.44   206.5 1070.81   236.0 1068.61   265.5 1064.88
     285 1062.03   295.0 1060.57     305 1060.03   322.2 1059.11   349.6 1062.67
   376.8 1073.74   404.1 1091.12   431.4 1109.69   458.7 1122.29   486.0 1132.23
   513.3 1143.99   540.6 1156.54   567.9 1167.30   595.2 1179.96
#Mann= 3 , 0 , 0
       0     0.1       0     285   0.045       0     305     0.1       0
Bank Sta=285,305
Exp/Cntr=0.3,0.1

Type RM Length L Ch R = 1 ,6851.5,249.8,250,245.1
XS GIS Cut Line= 3
     1692418.011      440188.452     1692237.294      440434.754
     1692007.695      440618.436
#Sta/Elev= 24
       0 1129.98    27.8 1121.72    55.5 1111.02    83.3 1099.04   111.1 1087.57
   138.9 1075.97   166.6 1064.63   194.4 1059.62   222.2 1057.33   250.0 1056.30
   277.7 1056.14   295.5 1056.36   305.5 1056.48   315.5 1059.15   334.9 1064.32
   364.3 1084.44   393.7 1099.78   423.1 1110.20   452.5 1118.58   481.9 1126.27
   511.3 1133.40   540.7 1144.61   570.1 1156.34   599.5 1169.00
#Mann= 3 , 0 , 0
       0     0.1       0   295.5   0.045       0   315.5     0.1       0
Bank Sta=295.5,315.5
Exp/Cntr=0.3,0.1

Type RM Length L Ch R = 1 ,6601.5,256.9,250,238.3
XS GIS Cut Line= 3
     1692245.558      440013.441     1692070.290      440253.453
     1691871.690      440474.012
#Sta/Elev= 23
       0 1153.76    29.7 1139.01    59.4 1128.71    89.2 1120.07   118.9 1112.89
   148.6 1102.00   178.3 1089.55   208.0 1078.00   237.8 1068.38   267.5 1059.54
   287.2 1054.96   297.2 1052.63   307.2 1052.48   326.9 1052.17   356.6 1054.44
   386.2 1056.07   415.9 1061.68   445.6 1073.31   475.3 1087.50   505.0 1102.99
   534.6 1115.38   564.3 1125.50   594.0 1132.78
#Mann= 3 , 0 , 0
       0     0.1       0   287.2   0.045       0   307.2     0.1       0
Bank Sta=287.2,307.2
Exp/Cntr=0.3,0.1

Type RM Length L Ch R = 1 ,6351.5,260.1,250,237.3
XS GIS Cut Line= 3
     1691950.516      439862.582     1691850.390      440140.707
     1691769.560      440426.085
#Sta/Elev= 23
       0 1189.18    29.6 1176.30    59.1 1162.48    88.7 1149.32   118.2 1136.78
   147.8 1124.98   177.4 1113.78   206.9 1100.94   236.5 1085.68   266.0 1063.62
   285.6 1055.01   295.6 1050.61   305.6 1049.78   325.3 1048.14   354.9 1049.82
   384.6 1052.33   414.2 1054.60   443.9 1061.09   473.6 1073.54   503.2 1090.44
   532.9 1106.37   562.5 1118.82   592.2 1128.73
#Mann= 3 , 0 , 0
       0     0.1       0   285.6   0.045       0   305.6     0.1       0
Bank Sta=285.6,305.6
Exp/Cntr=0.3,0.1

Type RM Length L Ch R = 1 ,6101.5,243.1,250,259.7
XS GIS Cut Line= 3
     1691582.739      439821.677     1691610.134      440121.043
     1691665.560      440411.983
#Sta/Elev= 24
       0 1113.77    27.3 1104.88    54.7 1100.39    82.0 1102.48   109.3 1102.83
   136.6 1096.71   164.0 1088.90   191.3 1080.80   218.6 1071.63   246.0 1060.42
   273.3 1049.31   290.6 1045.32   300.6 1043.02   310.6 1043.13   330.2 1043.35
   359.8 1047.45   389.5 1052.61   419.1 1059.91   448.7 1072.02   478.3 1088.85
   507.9 1102.88   537.6 1114.02   567.2 1123.02   596.8 1131.05
#Mann= 3 , 0 , 0
       0     0.1       0   290.6   0.045       0   310.6     0.1       0
Bank Sta=290.6,310.6
Exp/Cntr=0.3,0.1

Type RM Length L Ch R = 1 ,5851.5,257.2,250,243.1
XS GIS Cut Line= 3
     1691425.821      439786.635     1691368.817      440076.839
     1691311.814      440367.044
#Sta/Elev= 23
       0 1126.82    29.6 1120.02    59.2 1113.48    88.7 1102.62   118.3 1092.97
   147.9 1085.04   177.4 1074.77   207.0 1064.54   236.6 1059.54   266.2 1044.69
   285.8 1040.12   295.8 1037.79   305.8 1037.96   325.3 1038.28   354.9 1040.11
   384.5 1041.04   414.0 1042.36   443.6 1047.83   473.2 1063.76   502.8 1082.69
   532.4 1096.92   561.9 1106.59   591.5 1112.38
#Mann= 3 , 0 , 0
       0     0.1       0   285.8   0.045       0   305.8     0.1       0
Bank Sta=285.8,305.8
Exp/Cntr=0.3,0.1

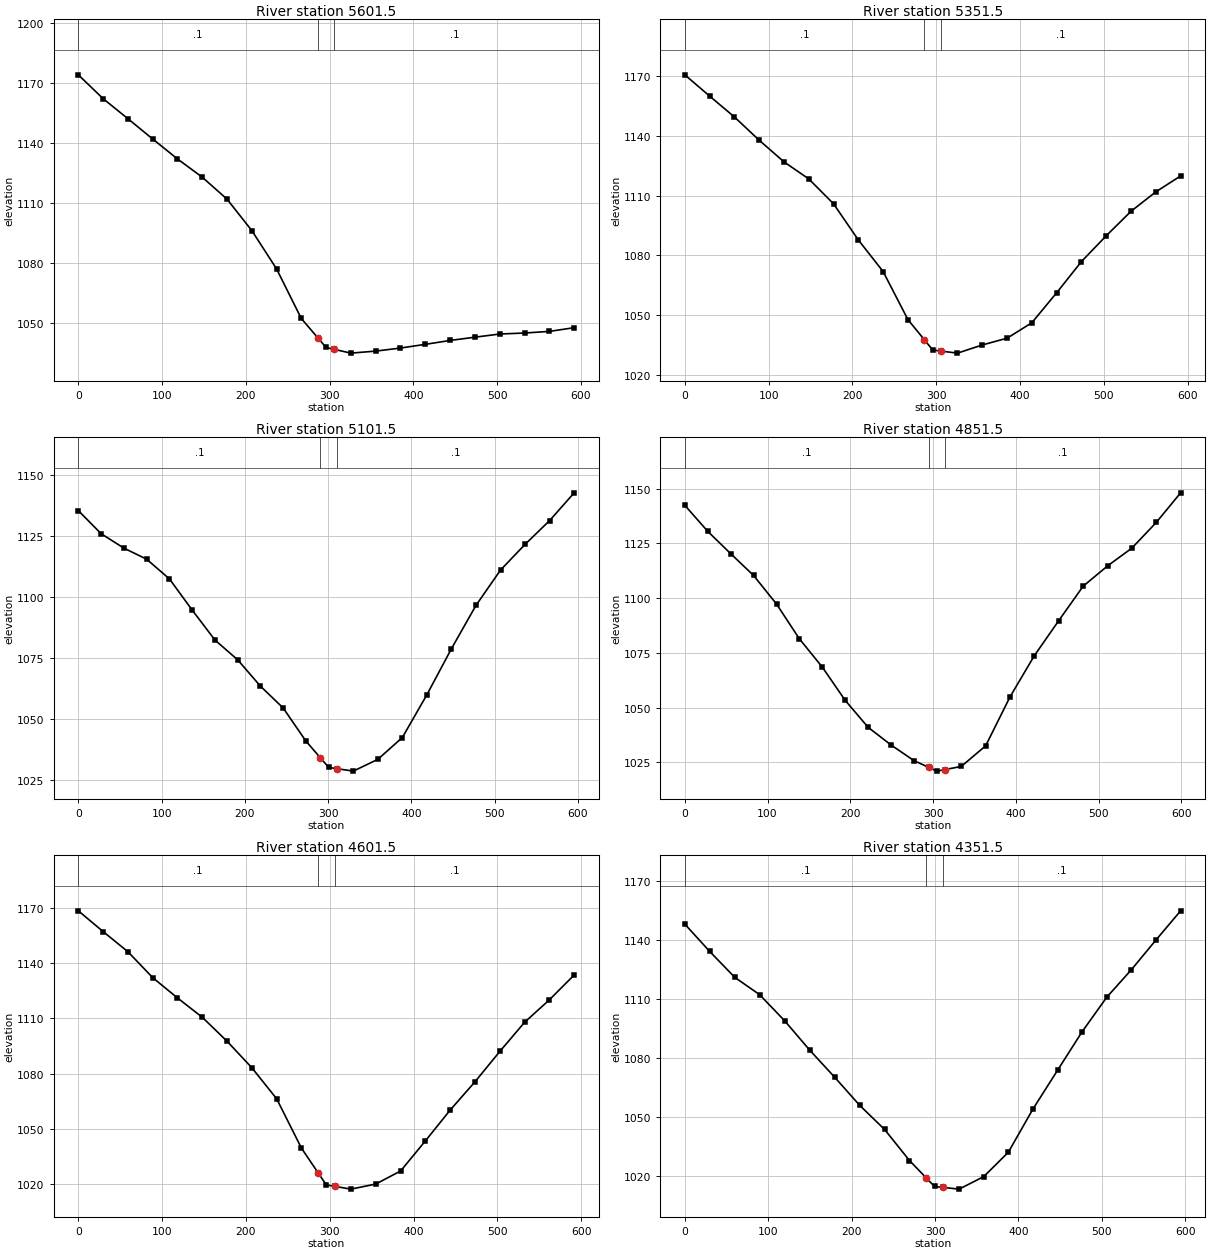
Type RM Length L Ch R = 1 ,5601.5,247.2,250,252.1
XS GIS Cut Line= 3
     1691094.889      439749.737     1691123.572      440044.039
     1691144.051      440339.426
#Sta/Elev= 23
       0 1174.25    29.6 1162.32    59.1 1152.32    88.7 1142.16   118.3 1132.17
   147.8 1123.07   177.4 1112.08   207.0 1096.36   236.6 1077.16   266.1 1052.34
   285.7 1042.74   295.7 1037.84   305.7 1036.88   325.3 1035.01   354.9 1036.02
   384.5 1037.55   414.1 1039.40   443.7 1041.35   473.4 1042.98   503.0 1044.57
   532.6 1045.07   562.2 1045.88   591.8 1047.74
#Mann= 3 , 0 , 0
       0     0.1       0   285.7   0.045       0   305.7     0.1       0
Bank Sta=285.7,305.7
Exp/Cntr=0.3,0.1

Type RM Length L Ch R = 1 ,5351.5,250.1,250,245.1
XS GIS Cut Line= 3
     1690879.730      439759.243     1690875.073      440054.957
     1690870.973      440350.679
#Sta/Elev= 23
       0 1170.53    29.6 1159.88    59.2 1149.39    88.7 1137.75   118.3 1126.89
   147.9 1118.33   177.4 1105.88   207.0 1087.74   236.6 1071.87   266.2 1047.77
   285.8 1037.67   295.8 1032.52   305.8 1031.99   325.3 1030.97   354.9 1035.07
   384.5 1038.46   414.0 1046.20   443.6 1061.23   473.2 1076.90   502.8 1089.84
   532.4 1102.13   561.9 1111.83   591.5 1119.83
#Mann= 3 , 0 , 0
       0     0.1       0   285.8   0.045       0   305.8     0.1       0
Bank Sta=285.8,305.8
Exp/Cntr=0.3,0.1

Type RM Length L Ch R = 1 ,5101.5,235.8,250,275.3
XS GIS Cut Line= 3
     1690629.100      439777.403     1690626.511      440078.177
     1690679.258      440368.283
#Sta/Elev= 24
       0 1135.54    27.3 1126.08    54.7 1120.15    82.0 1115.62   109.4 1107.54
   136.7 1094.78   164.1 1082.47   191.4 1074.36   218.8 1063.54   246.1 1054.59
   273.4 1041.03   290.8 1034.17   300.8 1030.23   310.8 1029.72   330.3 1028.72
   359.8 1033.56   389.2 1042.49   418.7 1060.04   448.2 1078.92   477.7 1096.69
   507.2 1111.18   536.7 1121.71   566.2 1131.47   595.6 1142.82
#Mann= 3 , 0 , 0
       0     0.1       0   290.8   0.045       0   310.8     0.1       0
Bank Sta=290.8,310.8
Exp/Cntr=0.3,0.1

Type RM Length L Ch R = 1 ,4851.5,250.2,250,242.7
XS GIS Cut Line= 3
     1690562.123      439758.587     1690400.587      440016.798
     1690182.291      440214.357
#Sta/Elev= 24
       0 1142.45    27.7 1130.55    55.4 1120.36    83.1 1110.37   110.8 1097.33
   138.4 1081.44   166.1 1068.51   193.8 1053.29   221.5 1040.98   249.2 1032.91
   276.9 1025.76   294.6 1022.70   304.6 1020.97   314.6 1021.70   334.0 1023.11
   363.5 1032.56   392.9 1054.91   422.3 1073.74   451.8 1089.76   481.2 1105.46
   510.7 1114.74   540.1 1122.88   569.6 1134.62   599.0 1148.14
#Mann= 3 , 0 , 0
       0     0.1       0   294.6   0.045       0   314.6     0.1       0
Bank Sta=294.6,314.6
Exp/Cntr=0.3,0.1

Type RM Length L Ch R = 1 ,4601.5,248.9,250,249.5
XS GIS Cut Line= 3
     1690361.835      439607.382     1690207.464      439859.647
     1690053.092      440111.912
#Sta/Elev= 23
       0 1168.60    29.6 1157.30    59.2 1146.32    88.7 1132.25   118.3 1121.17
   147.9 1110.65   177.4 1097.63   207.0 1083.18   236.6 1066.29   266.2 1039.40
   285.8 1026.17   295.8 1019.42   305.8 1018.64   325.3 1017.12   354.9 1019.90
   384.5 1027.01   414.0 1043.36   443.6 1060.16   473.2 1075.55   502.8 1092.06
   532.4 1107.95   561.9 1120.14   591.5 1133.67
#Mann= 3 , 0 , 0
       0     0.1       0   285.8   0.045       0   305.8     0.1       0
Bank Sta=285.8,305.8
Exp/Cntr=0.3,0.1

Type RM Length L Ch R = 1 ,4351.5,250.9,250,250.6
XS GIS Cut Line= 3
     1690153.206      439496.199     1689985.971      439744.520
     1689836.975      439999.253
#Sta/Elev= 23
       0 1148.16    29.9 1134.23    59.9 1121.06    89.8 1112.22   119.8 1098.91
   149.7 1084.04   179.6 1070.27   209.6 1055.95   239.5 1043.65   269.4 1027.82
   289.4 1019.01   299.4 1014.61   309.4 1014.15   328.9 1013.26   358.4 1019.62
   387.9 1032.02   417.4 1054.01   446.9 1073.74   476.4 1093.38   506.0 1110.98
   535.5 1124.97   565.0 1140.11   594.5 1154.92
#Mann= 3 , 0 , 0
       0     0.1       0   289.4   0.045       0   309.4     0.1       0
Bank Sta=289.4,309.4
Exp/Cntr=0.3,0.1

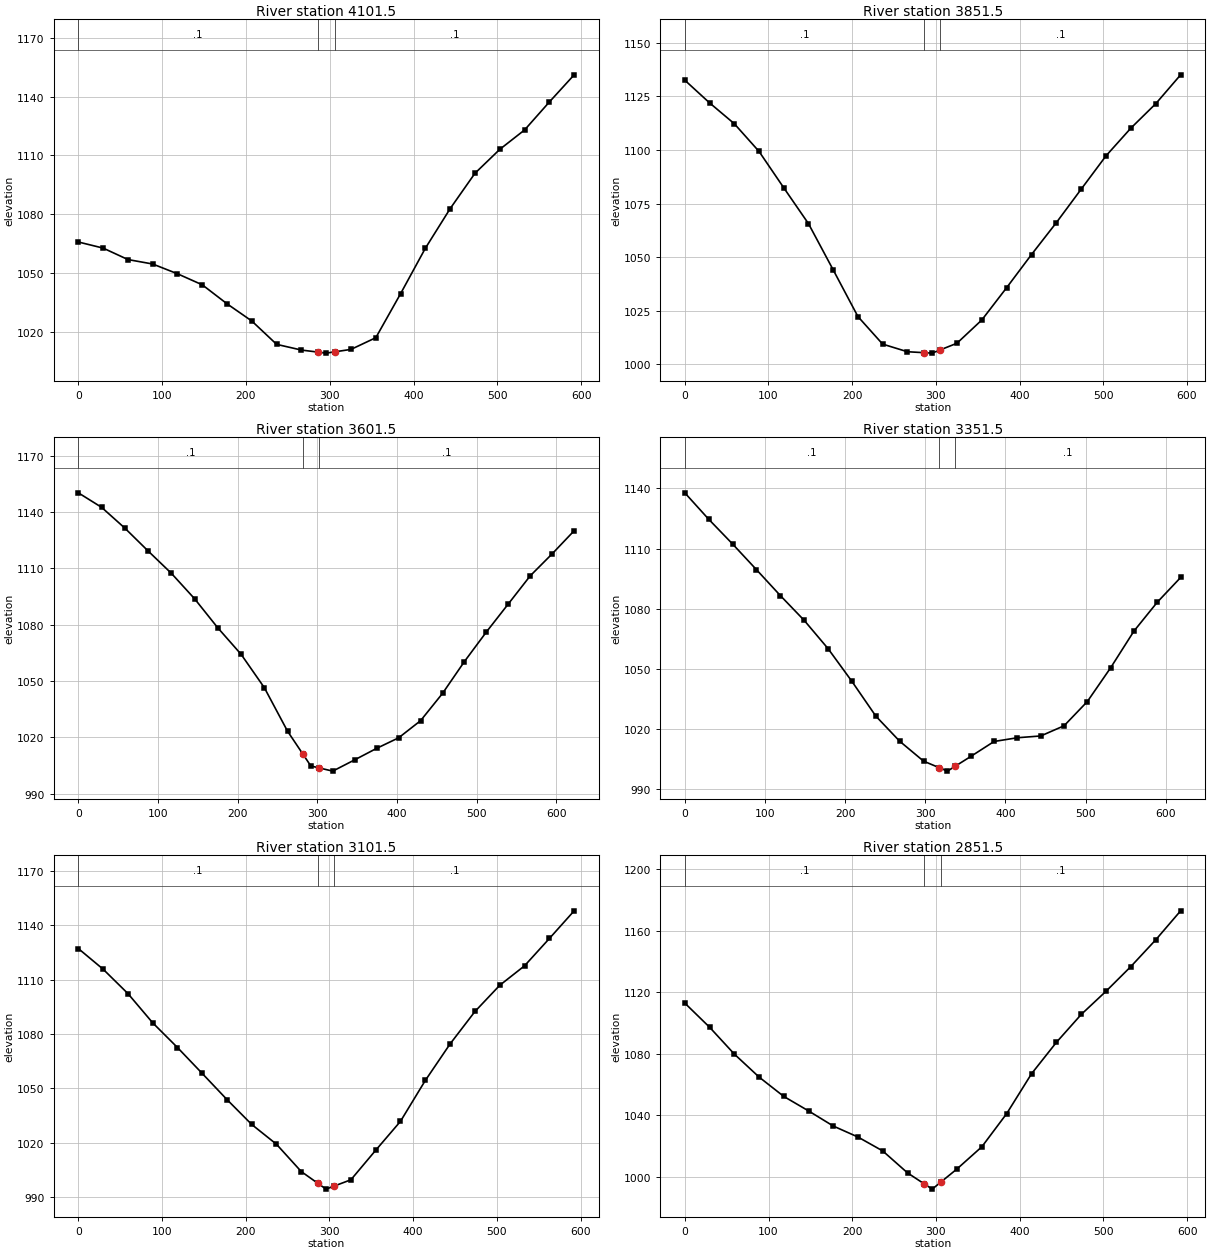
Type RM Length L Ch R = 1 ,4101.5,248.2,250,250.6
XS GIS Cut Line= 3
     1689947.461      439335.913     1689792.226      439587.647
     1689636.863      439839.302
#Sta/Elev= 23
       0 1065.73    29.6 1062.61    59.2 1056.76    88.7 1054.49   118.3 1049.50
   147.9 1043.86   177.4 1034.17   207.0 1025.37   236.6 1013.46   266.2 1010.55
   285.8 1009.52   295.8 1008.99   305.8 1009.64   325.3 1010.90   354.9 1016.87
   384.5 1039.39   414.0 1062.55   443.6 1082.78   473.2 1100.83   502.8 1113.04
   532.4 1122.95   561.9 1137.21   591.5 1151.08
#Mann= 3 , 0 , 0
       0     0.1       0   285.8   0.045       0   305.8     0.1       0
Bank Sta=285.8,305.8
Exp/Cntr=0.3,0.1

Type RM Length L Ch R = 1 ,3851.5,265.7,250,236.3
XS GIS Cut Line= 3
     1689758.822      439205.815     1689586.674      439446.047
     1689423.619      439694.181
#Sta/Elev= 23
       0 1132.60    29.6 1122.01    59.1 1112.30    88.7 1099.34   118.2 1082.39
   147.8 1065.60   177.3 1044.04   206.9 1022.21   236.4 1009.35   266.0 1005.79
   285.5 1005.36   295.5 1005.14   305.5 1006.69   325.2 1009.75   354.9 1020.61
   384.6 1035.71   414.3 1051.18   444.0 1066.08   473.7 1081.73   503.4 1097.30
   533.1 1110.24   562.8 1121.63   592.5 1135.11
#Mann= 3 , 0 , 0
       0     0.1       0   285.5   0.045       0   305.5     0.1       0
Bank Sta=285.5,305.5
Exp/Cntr=0.3,0.1

Type RM Length L Ch R = 1 ,3601.5,238,250,272.6
XS GIS Cut Line= 3
     1689376.575      439045.385     1689380.252      439337.158
     1689361.475      439667.141
#Sta/Elev= 25
       0 1150.17    29.2 1142.45    58.4 1131.36    87.5 1119.23   116.7 1107.33
   145.9 1093.75   175.1 1078.23   204.3 1064.15   233.4 1046.42   262.6 1023.19
   281.8 1011.03   291.8 1004.69   301.8 1003.69   319.3 1001.94   346.9 1007.96
   374.4 1014.07   402.0 1019.68   429.5 1028.79   457.1 1043.34   484.6 1060.33
   512.1 1076.04   539.7 1091.02   567.2 1105.98   594.8 1117.72   622.3 1129.98
#Mann= 3 , 0 , 0
       0     0.1       0   281.8   0.045       0   301.8     0.1       0
Bank Sta=281.8,301.8
Exp/Cntr=0.3,0.1

Type RM Length L Ch R = 1 ,3351.5,239,250,245.5
XS GIS Cut Line= 3
     1689315.796      439030.698     1689169.698      439324.023
     1688930.266      439489.257
#Sta/Elev= 24
       0 1137.83    29.8 1124.65    59.6 1112.30    89.4 1099.49   119.2 1086.56
   149.0 1074.17   178.7 1060.10   208.5 1043.74   238.3 1026.43   268.1 1013.88
   297.9 1003.94   317.7 1000.63   327.7  998.96   337.7 1001.48   356.8 1006.29
   385.9 1013.76   415.0 1015.62   444.1 1016.51   473.2 1021.59   502.2 1033.68
   531.3 1050.54   560.4 1068.86   589.5 1083.26   618.6 1095.58
#Mann= 3 , 0 , 0
       0     0.1       0   317.7   0.045       0   337.7     0.1       0
Bank Sta=317.7,337.7
Exp/Cntr=0.3,0.1

Type RM Length L Ch R = 1 ,3101.5,252.7,250,248.6
XS GIS Cut Line= 3
     1689227.760      438945.474     1689003.291      439138.284
     1688791.015      439345.149
#Sta/Elev= 23
       0 1127.23    29.6 1115.84    59.2 1102.40    88.8 1086.26   118.4 1072.62
   148.0 1058.30   177.6 1043.87   207.1 1030.16   236.7 1019.23   266.3 1004.16
   285.9  997.74   295.9  994.46   305.9  996.20   325.6  999.62   355.2 1015.90
   384.8 1031.86   414.5 1054.44   444.1 1074.60   473.8 1092.50   503.4 1106.95
   533.0 1117.69   562.7 1132.78   592.3 1148.05
#Mann= 3 , 0 , 0
       0     0.1       0   285.9   0.045       0   305.9     0.1       0
Bank Sta=285.9,305.9
Exp/Cntr=0.3,0.1

Type RM Length L Ch R = 1 ,2851.5,246,250,249.7
XS GIS Cut Line= 3
     1689017.806      438758.011     1688817.097      438974.912
     1688615.167      439192.218
#Sta/Elev= 23
       0 1112.95    29.6 1097.28    59.1 1079.86    88.7 1064.91   118.2 1052.33
   147.8 1042.92   177.3 1033.10   206.9 1025.93   236.4 1016.92   266.0 1002.67
   285.5  995.69   295.5  992.11   305.5  996.54   325.2 1005.26   354.8 1019.63
   384.5 1041.20   414.2 1067.11   443.8 1087.43   473.5 1105.58   503.2 1120.70
   532.8 1136.71   562.5 1154.06   592.2 1172.88
#Mann= 3 , 0 , 0
       0     0.1       0   285.5   0.045       0   305.5     0.1       0
Bank Sta=285.5,305.5
Exp/Cntr=0.3,0.1

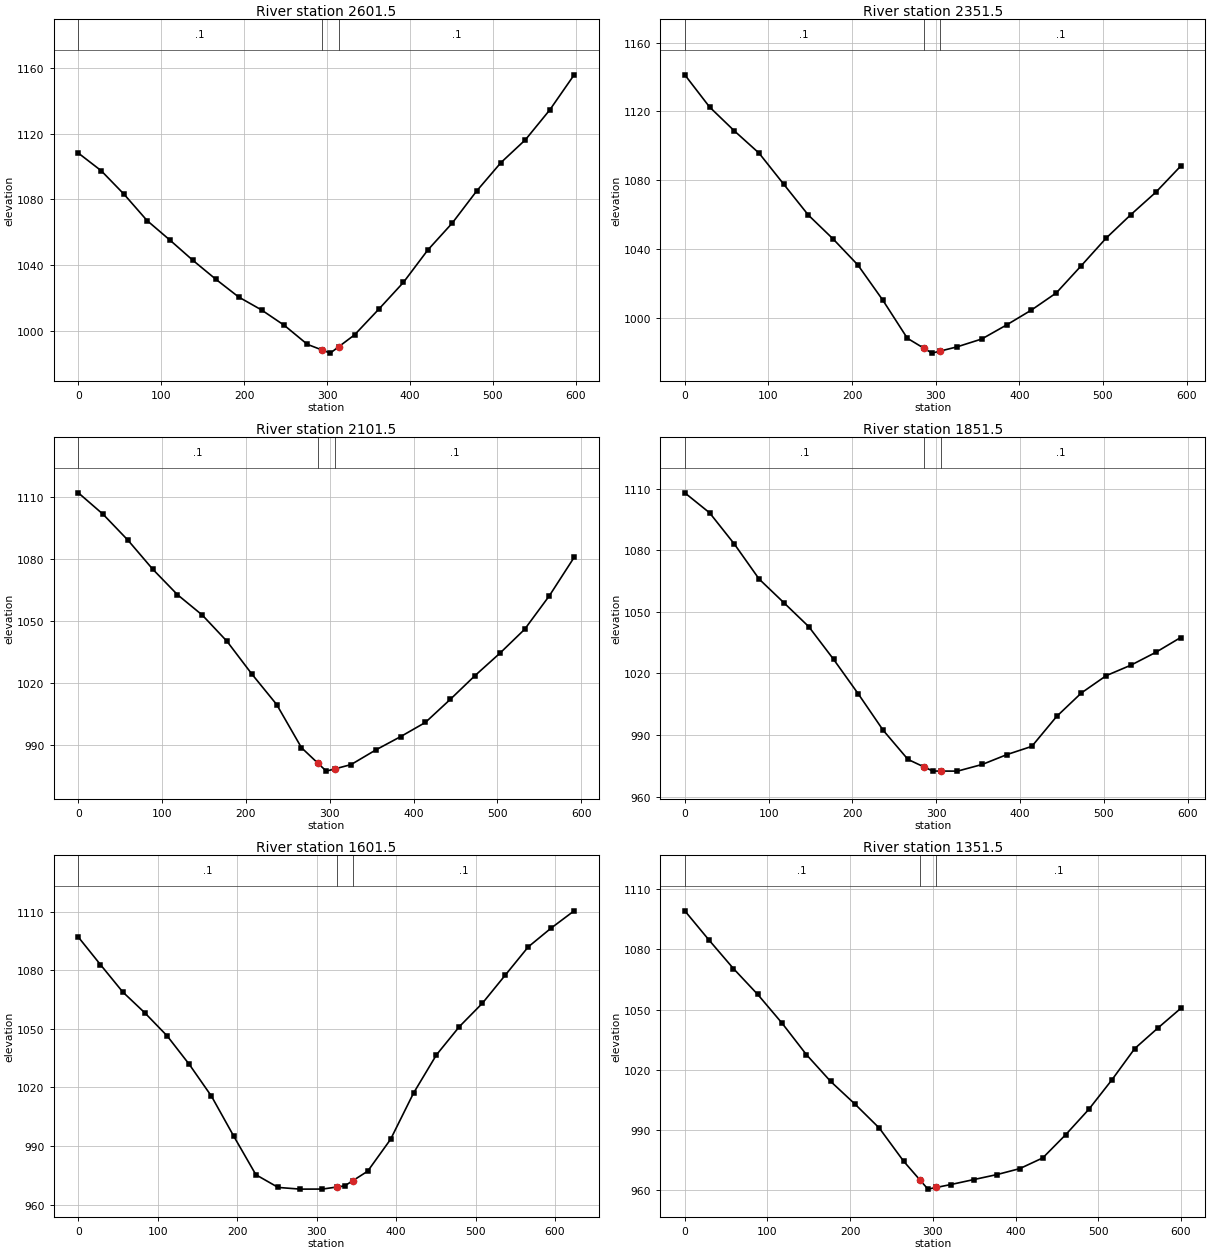
Type RM Length L Ch R = 1 ,2601.5,248.5,250,254.5
XS GIS Cut Line= 3
     1688881.466      438609.400     1688643.484      438798.400
     1688442.879      439013.753
#Sta/Elev= 24
       0 1108.13    27.6 1097.42    55.3 1083.05    82.9 1067.18   110.5 1055.31
   138.1 1043.08   165.8 1031.58   193.4 1020.78   221.0 1012.92   248.6 1003.53
   276.3  992.03   293.9  988.63   303.9  986.70   313.9  990.48   333.3  997.82
   362.8 1013.54   392.2 1029.63   421.6 1049.28   451.1 1065.63   480.5 1085.07
   509.9 1102.37   539.4 1116.22   568.8 1134.33   598.2 1155.63
#Mann= 3 , 0 , 0
       0     0.1       0   293.9   0.045       0   313.9     0.1       0
Bank Sta=293.9,313.9
Exp/Cntr=0.3,0.1

Type RM Length L Ch R = 1 ,2351.5,263.5,250,236.5
XS GIS Cut Line= 3
     1688772.573      438409.929     1688530.629      438579.807
     1688290.073      438754.399
#Sta/Elev= 23
       0 1141.35    29.6 1122.62    59.1 1108.76    88.7 1095.78   118.2 1077.69
   147.8 1059.63   177.4 1045.72   206.9 1030.62   236.5 1010.31   266.1  987.92
   285.6  982.19   295.6  979.25   305.6  980.47   325.4  982.88   355.1  987.48
   384.8  995.66   414.5 1004.34   444.2 1014.31   474.0 1030.12   503.7 1046.17
   533.4 1059.92   563.1 1072.89   592.9 1088.14
#Mann= 3 , 0 , 0
       0     0.1       0   285.6   0.045       0   305.6     0.1       0
Bank Sta=285.6,305.6
Exp/Cntr=0.3,0.1

Type RM Length L Ch R = 1 ,2101.5,247.1,250,252.3
XS GIS Cut Line= 3
     1688454.595      438161.342     1688335.293      438431.962
     1688216.582      438702.842
#Sta/Elev= 23
       0 1112.19    29.6 1101.76    59.2 1089.22    88.7 1075.19   118.3 1062.80
   147.9 1052.92   177.4 1040.18   207.0 1024.34   236.6 1009.57   266.2  988.64
   285.8  981.12   295.8  977.28   305.8  978.35   325.3  980.44   354.9  987.56
   384.5  994.01   414.0 1000.88   443.6 1012.02   473.2 1023.58   502.8 1034.39
   532.4 1046.02   561.9 1062.28   591.5 1080.92
#Mann= 3 , 0 , 0
       0     0.1       0   285.8   0.045       0   305.8     0.1       0
Bank Sta=285.8,305.8
Exp/Cntr=0.3,0.1

Type RM Length L Ch R = 1 ,1851.5,243.5,250,253.2
XS GIS Cut Line= 3
     1688270.113      438045.410     1688123.785      438302.424
     1687977.456      438559.437
#Sta/Elev= 23
       0 1107.95    29.6 1098.21    59.2 1082.96    88.7 1065.95   118.3 1054.40
   147.9 1042.78   177.4 1026.93   207.0 1010.02   236.6  992.36   266.2  978.15
   285.8  974.40   295.8  972.48   305.8  972.47   325.3  972.44   354.9  975.70
   384.5  980.53   414.0  984.50   443.6  999.06   473.2 1010.54   502.8 1018.94
   532.4 1024.07   561.9 1030.29   591.5 1037.48
#Mann= 3 , 0 , 0
       0     0.1       0   285.8   0.045       0   305.8     0.1       0
Bank Sta=285.8,305.8
Exp/Cntr=0.3,0.1

Type RM Length L Ch R = 1 ,1601.5,244.5,250,262.8
XS GIS Cut Line= 3
     1688127.849      437968.410     1687894.572      438209.237
     1687720.312      438439.505
#Sta/Elev= 25
       0 1097.11    27.9 1082.95    55.9 1068.98    83.8 1058.23   111.8 1046.45
   139.7 1031.82   167.6 1015.53   195.6  995.06   223.5  975.28   251.5  968.77
   279.4  967.90   307.3  967.93   325.3  968.98   335.3  969.57   345.3  972.17
   364.2  977.09   393.0  993.41   421.9 1017.11   450.8 1036.76   479.7 1051.24
   508.6 1063.20   537.4 1077.61   566.3 1092.08   595.2 1101.74   624.1 1110.57
#Mann= 3 , 0 , 0
       0     0.1       0   325.3   0.045       0   345.3     0.1       0
Bank Sta=325.3,345.3
Exp/Cntr=0.3,0.1

Type RM Length L Ch R = 1 ,1351.5,240.2,250,254.5
XS GIS Cut Line= 3
     1688051.366      437822.135     1687807.844      437986.871
     1687526.307      438105.787
#Sta/Elev= 24
       0 1099.14    29.4 1084.53    58.8 1070.40    88.2 1057.52   117.6 1043.23
   147.0 1027.59   176.4 1014.22   205.8 1002.94   235.2  991.01   264.6  974.53
     284  965.35   294.0  960.62     304  961.44   321.8  962.91   349.6  965.39
   377.4  967.85   405.1  970.83   432.9  976.16   460.7  987.75   488.5 1000.30
   516.3 1014.90   544.1 1030.58   571.8 1040.70   599.6 1050.53
#Mann= 3 , 0 , 0
       0     0.1       0     284   0.045       0     304     0.1       0
Bank Sta=284,304
Exp/Cntr=0.3,0.1