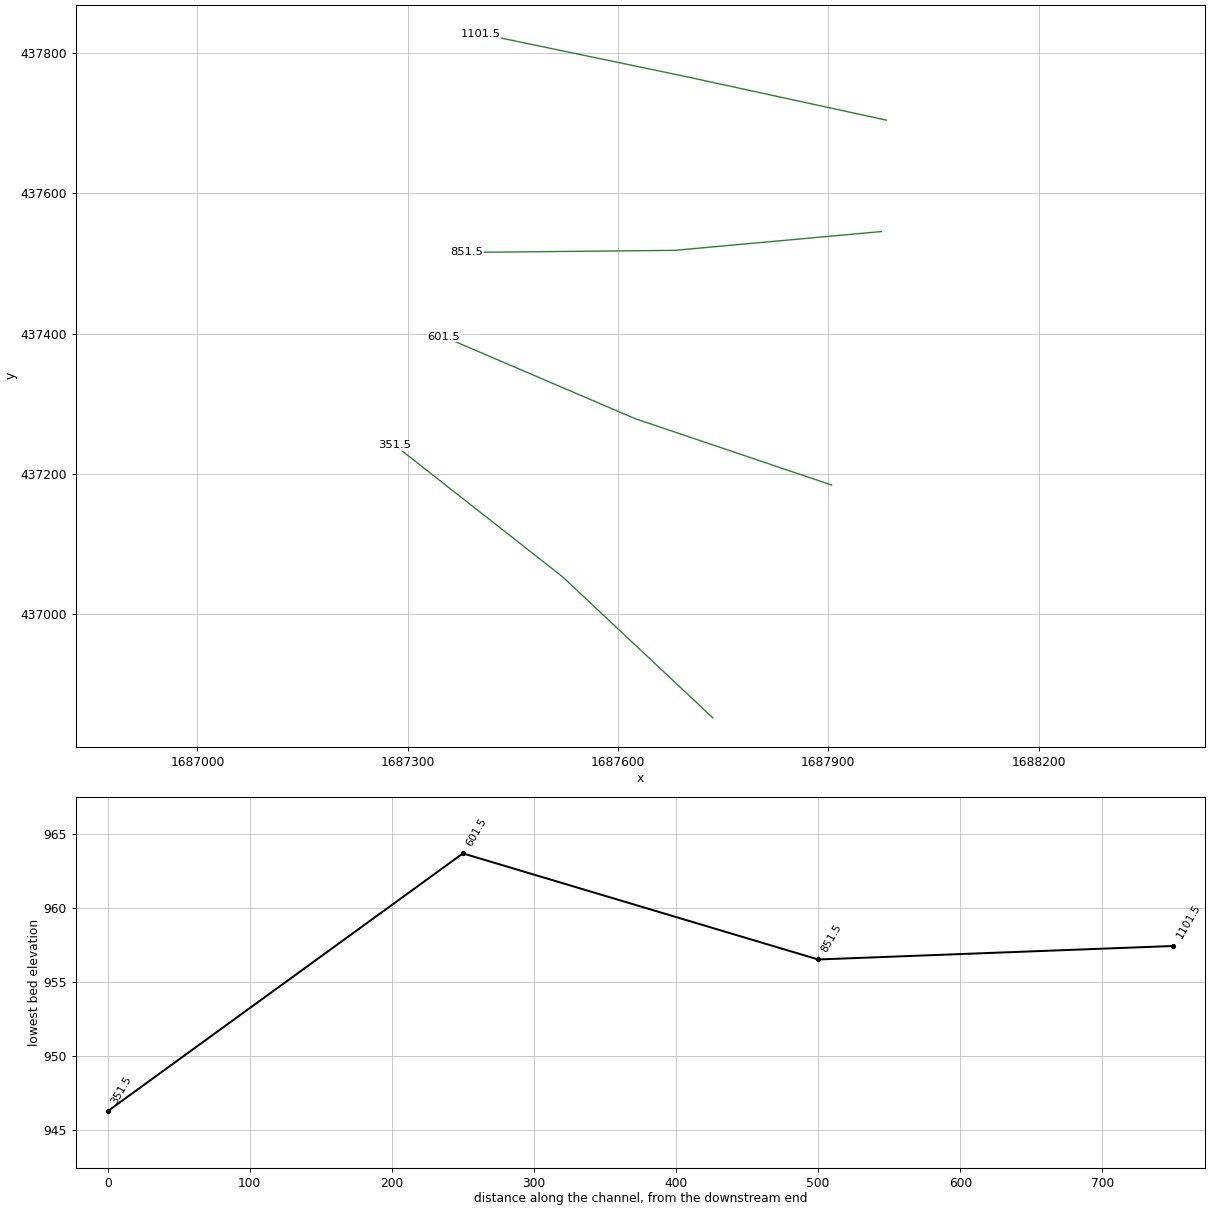
HEC-RAS study BROWNSRN.prj: BROWNSRN

--- BROWNSRN.g01 (geometry) --- (continued)

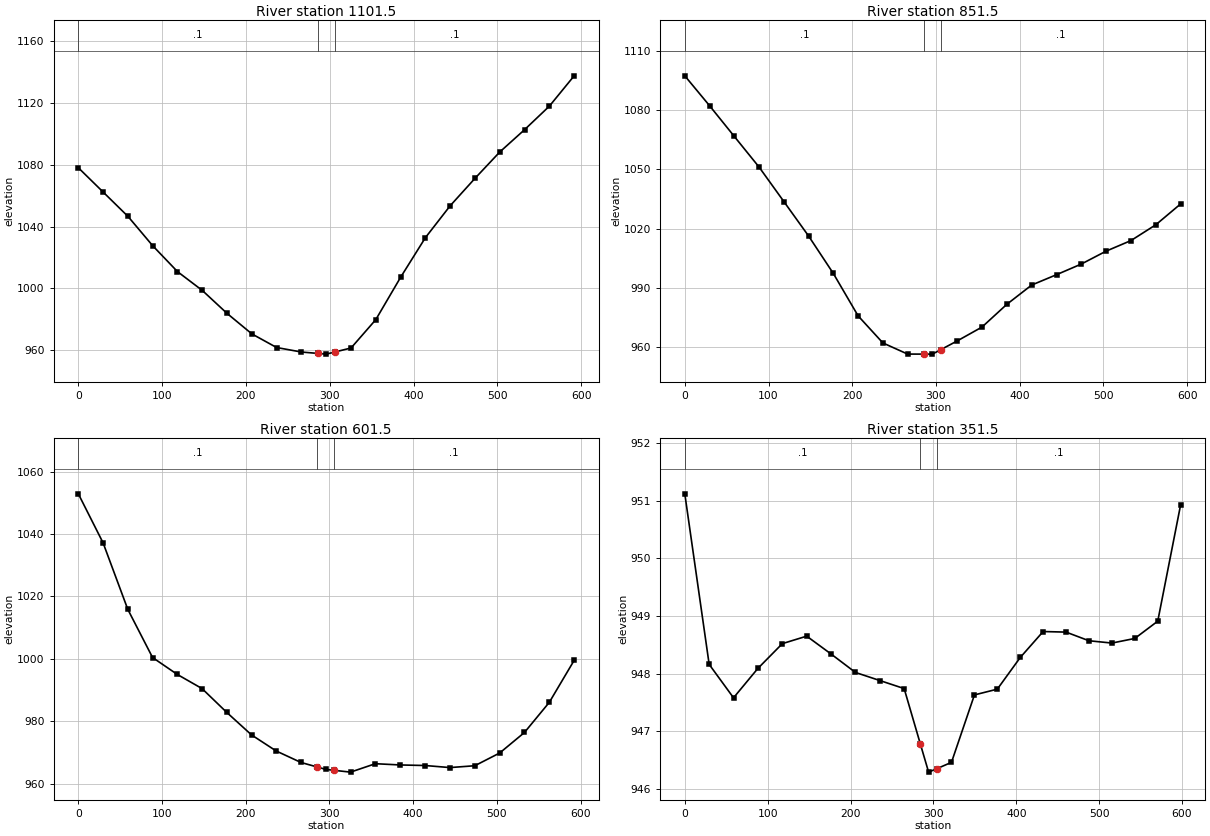
Type RM Length L Ch R = 1 ,1101.5,242.2,250,255.3
XS GIS Cut Line= 3
     1687982.759      437704.602     1687693.701      437767.366
     1687404.171      437827.720
#Sta/Elev= 23
       0 1078.08    29.6 1062.34    59.2 1046.60    88.7 1027.62   118.3 1010.84
   147.9  998.66   177.5  983.77   207.1  970.51   236.6  961.70   266.2  958.79
   285.8  957.89   295.8  957.43   305.8  958.77   325.4  961.41   354.9  979.74
   384.5 1007.14   414.1 1032.82   443.7 1053.49   473.2 1071.17   502.8 1088.25
   532.4 1102.70   562.0 1117.94   591.6 1137.58
#Mann= 3 , 0 , 0
       0     0.1       0   285.8   0.045       0   305.8     0.1       0
Bank Sta=285.8,305.8
Exp/Cntr=0.3,0.1

Type RM Length L Ch R = 1 ,851.5,260.3,250,239.3
XS GIS Cut Line= 3
     1687975.511      437545.633     1687681.040      437518.829
     1687384.531      437515.876
#Sta/Elev= 23
       0 1097.20    29.6 1082.08    59.1 1066.58    88.7 1051.08   118.3 1033.66
   147.8 1016.26   177.4  997.30   207.0  975.86   236.6  962.17   266.1  956.55
   285.7  956.53   295.7  956.52   305.7  958.77   325.3  963.18   355.0  970.21
   384.6  981.69   414.3  991.44   444.0  996.68   473.6 1002.06   503.2 1008.58
   532.9 1013.93   562.6 1021.92   592.2 1032.44
#Mann= 3 , 0 , 0
       0     0.1       0   285.7   0.045       0   305.7     0.1       0
Bank Sta=285.7,305.7
Exp/Cntr=0.3,0.1

Type RM Length L Ch R = 1 ,601.5,260.5,250,243.2
XS GIS Cut Line= 3
     1687904.669      437184.074     1687624.661      437278.662
     1687351.754      437395.501
#Sta/Elev= 23
       0 1052.91    29.6 1037.17    59.1 1015.86    88.7 1000.42   118.2  995.00
   147.8  990.46   177.3  982.83   206.9  975.61   236.4  970.45   266.0  966.77
   285.6  965.30   295.6  964.55   305.6  964.25   325.2  963.67   354.9  966.37
   384.6  965.97   414.3  965.79   444.0  965.13   473.7  965.72   503.4  969.80
   533.0  976.38   562.7  986.05   592.4  999.51
#Mann= 3 , 0 , 0
       0     0.1       0   285.6   0.045       0   305.6     0.1       0
Bank Sta=285.6,305.6
Exp/Cntr=0.3,0.1

Type RM Length L Ch R = 1 ,351.5,354.4,351.5,344.9
XS GIS Cut Line= 3
     1687735.353      436851.875     1687520.889      437053.196
     1687281.541      437240.904
#Sta/Elev= 24
       0  951.12    29.4  948.16    58.8  947.58    88.2  948.09   117.7  948.52
   147.1  948.65   176.5  948.34   205.9  948.02   235.3  947.88   264.7  947.74
   284.2  946.78   294.2  946.29   304.2  946.35   321.8  946.46   349.5  947.63
   377.1  947.73   404.8  948.28   432.4  948.73   460.1  948.72   487.7  948.57
   515.4  948.53   543.0  948.61   570.7  948.91   598.3  950.93
#Mann= 3 , 0 , 0
       0     0.1       0   284.2   0.045       0   304.2     0.1       0
Bank Sta=284.2,304.2
Exp/Cntr=0.3,0.1